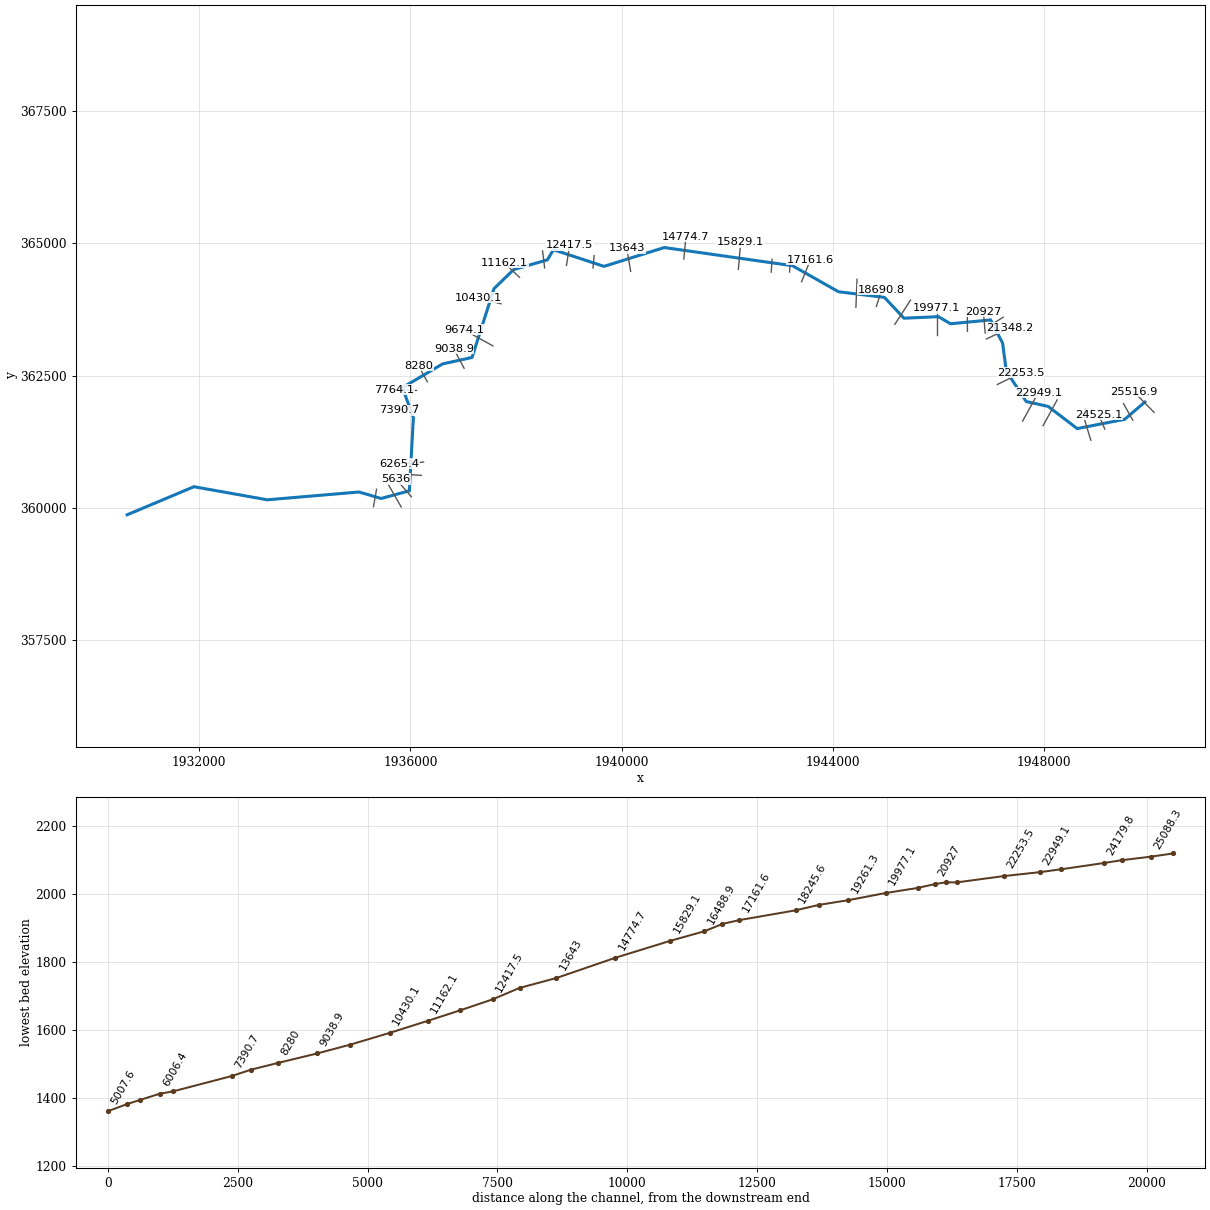
--- DGHTRTYRN.prj (project) ---

Proj Title=DGHTRTYRN
Current Plan=p01
Geom File=g01
Flow File=f01
Plan File=p01
DSS Export Rating Curves=0
DSS Export Rating Curve Sorted=0
DSS Export Volume Flow Curves=0
DXF OffsetX=0
DXF OffsetY=0
DXF ScaleX=0
DXF ScaleY=0

--- DGHTRTYRN.p01 (plan) ---

Plan Title=Floodplain
Program Version=4.00
Geom File=g01
Flow File=f01
K Sum by GR=0
Std Step Tol=0.01
Critical Tol=0.01
Num of Std Step Trials=20
Max Error Tol=0.3
Flow Tol Ratio=0.001
Split Flow NTrial=30
Split Flow Tol=0.02
Split Flow Ratio=0.02
Log Output Level=0
Friction Slope Method=1
Unsteady Friction Slope Method=2
Unsteady Bridges Friction Slope Method=1
Global Log Level=0
CheckData=False
Run HTab=0
Run UNet=0
Run PostProcess=0
UNET Theta=0
UNET Theta Warmup=0
UNET ZTol=0
UNET ZSATol=0
UNET MxIter=0
UNET MaxInSteps=0
UNET DtIC=0
UNET DtMin=0
UNET MaxCRTS=0
UNET WFStab=0
UNET SFStab=0
UNET WFX=0
UNET SFX=0
UNET DSS MLevel=0
UNET DZMax Abort=0
UNET Convert EG Bridges=0
UNET Use Existing IB Tables=0
UNET Froude Limit=0
UNET Froude Power=0
Write IC File=0
Echo Input=False
Echo Output=False
Write Detailed=0

--- DGHTRTYRN.f01 (steady flow) ---

Flow Title=NFF Regression Equation
Program Version=4.10
Number of Profiles= 1
Profile Names=P100yr
River Rch & RM=DGHTRTYRN,Main            ,25516.9
517.6409
River Rch & RM=DGHTRTYRN,Main            ,23354
539.3614
River Rch & RM=DGHTRTYRN,Main            ,22949.1
907.6646
River Rch & RM=DGHTRTYRN,Main            ,21136.1
966.9668
River Rch & RM=DGHTRTYRN,Main            ,20602
1152.586
River Rch & RM=DGHTRTYRN,Main            ,17161.6
1239.099
River Rch & RM=DGHTRTYRN,Main            ,8280
1376.607
River Rch & RM=DGHTRTYRN,Main            ,6006.4
1527.393
River Rch & RM=DGHTRTYRN,Main            ,5376.7
1661.547
River Rch & RM=DGHTRTYRN,Main            ,216.4
1770.558
Boundary for River Rch & Prof#=DGHTRTYRN,Main            , 1
Up Type= 0
Dn Type= 3
Dn Slope=0.01772
DSS Import GetInterval= 0
DSS Import GetPeak= 0
DSS Import FillOption= 0

--- DGHTRTYRN.g01 (geometry) ---

Geom Title=USGS 10m DEM
Program Version=4.10

River Reach=DGHTRTYRN       ,Main
Reach XY= 30
     1949910.014      362000.083     1949527.592      361673.027
     1948627.502      361498.391     1948076.704      361916.723
     1947661.079      362009.171     1947284.777      362584.692
     1947214.204      363112.817     1946987.642      363549.796
     1946227.225      363476.879      1945999.36      363610.994
     1945345.715      363582.348     1944976.096      363975.577
     1944106.305       364081.48     1943235.819      364572.799
      1940807.19      364916.194      1939665.58      364560.829
     1938707.535      364874.725     1938592.306      364683.445
     1937954.159      364499.636     1937581.488      364139.886
     1937165.872      362840.786     1936606.503      362718.542
     1935847.406      362271.465     1936054.998       361707.81
     1935979.177      360323.499     1935442.982      360178.624
     1935025.409       360301.23      1933288.66      360153.747
     1931898.534      360400.637     1930633.594      359870.633

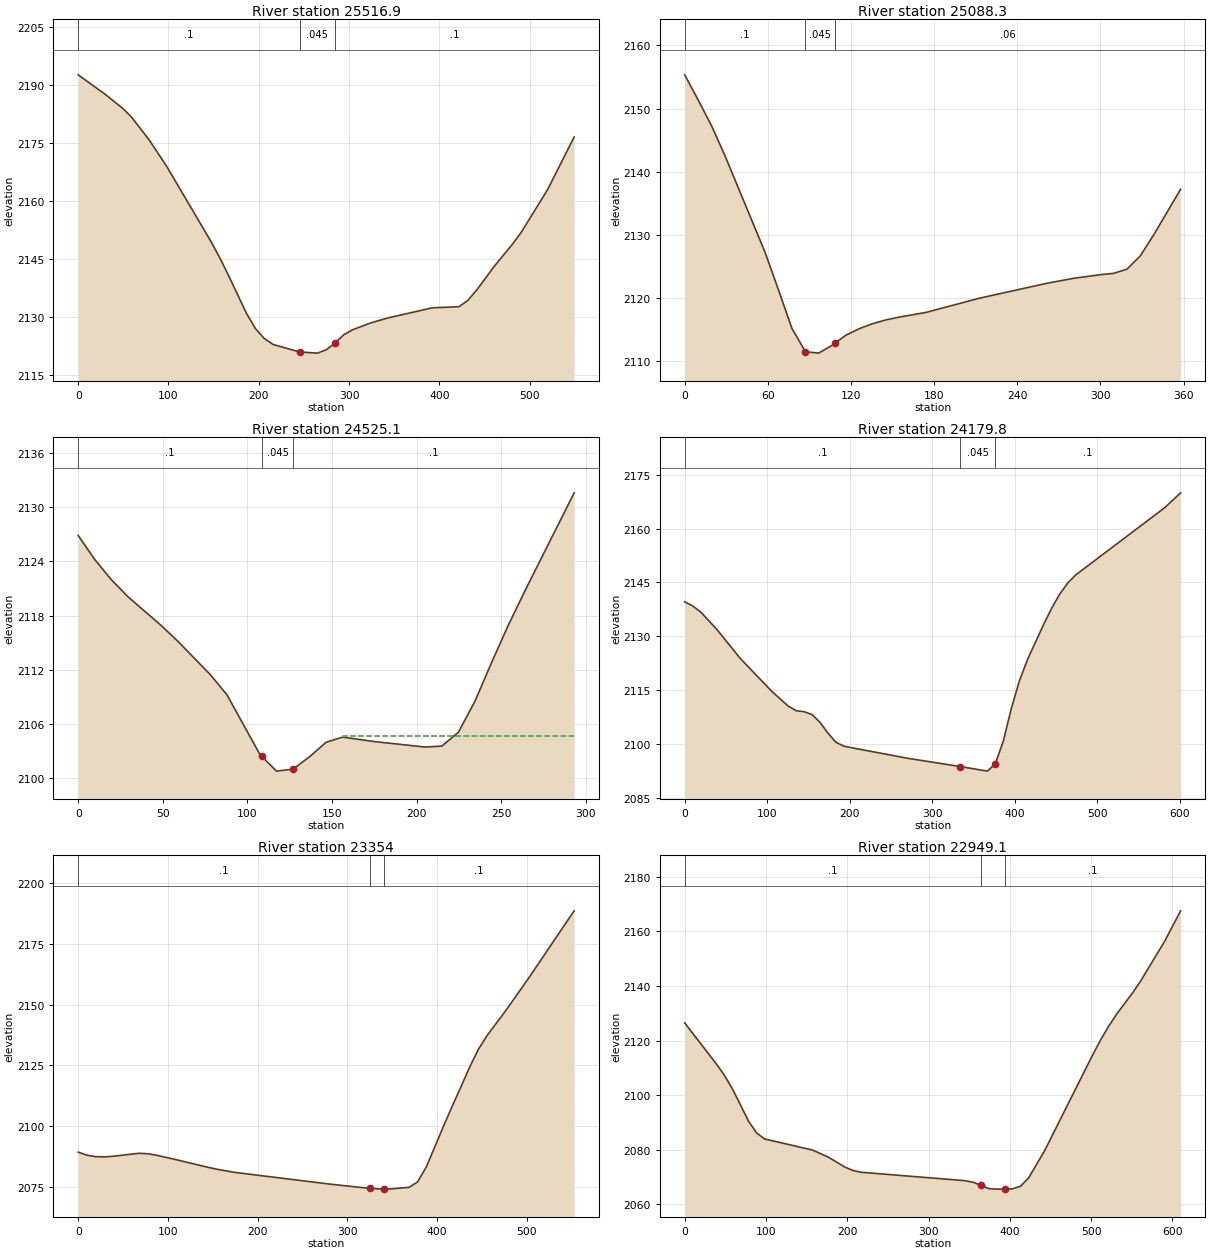
Type RM Length L Ch R = 1 ,25516.9 ,437.4,428.7,422
XS GIS Cut Line= 2
     1950083.456      361805.186     1949697.171      362195.811
#Sta/Elev= 30
       0 2192.55    29.4  2187.6      49 2183.96    58.9 2181.68    78.5 2175.79
    98.1 2168.89   147.2 2149.47     157 2145.25   166.8 2140.64   186.4 2130.99
   196.2 2127.11     206 2124.52   215.8 2122.97   245.2 2121.02   264.9 2120.72
   274.7 2121.57   284.5 2123.32   294.3 2125.48   304.1 2126.76   323.7 2128.49
   343.4 2129.82   392.4 2132.42   421.8  2132.7   431.6 2134.32   441.5 2137.02
   461.1 2143.19   480.7 2148.73   490.5  2151.8   519.9 2162.89   549.4 2176.51
#Mann= 3 , 0 , 0
       0      .1       0   245.2    .045       0   284.5      .1       0
Bank Sta=245.2,284.5
XS Rating Curve= 0 ,0
Exp/Cntr=0.3,0.1

Type RM Length L Ch R = 1 ,25088.3 ,565.7,563.1,568.5
XS GIS Cut Line= 2
     1949678.942      361657.616     1949504.463      361970.116
#Sta/Elev= 26
       0 2155.34     9.7 2151.37    19.4 2147.26      29 2142.56      58 2127.22
    67.7 2121.25    77.4 2115.15    87.1 2111.46    96.7 2111.23   106.4 2112.46
   108.8 2112.85   116.1 2114.04   125.8 2115.09   135.4 2115.88   145.1 2116.49
   154.8 2116.94   174.1 2117.68   212.8 2119.94   261.2 2122.29   280.5 2123.08
   299.9 2123.66   309.5 2123.87   319.2 2124.54   328.9 2126.67   338.6 2130.02
   357.9 2137.21
#Mann= 3 , 0 , 0
       0      .1       0    87.1    .045       0   108.8     .06       0
Bank Sta=87.1,108.8
XS Rating Curve= 0 ,0
Exp/Cntr=0.3,0.1

Type RM Length L Ch R = 1 ,24525.1 ,349.3,345.4,330.9
XS GIS Cut Line= 2
     1949150.296      361488.346     1949038.317      361759.179
#Sta/Elev= 24
       0 2126.85     9.8 2124.19    19.5 2121.98    29.3  2120.1    48.8 2116.94
    58.6 2115.21    78.2 2111.44    87.9 2109.24   107.5 2102.61   108.5 2102.42
   117.2  2100.8     127 2101.02   136.8  2102.4   146.5 2103.99   156.3 2104.56
   175.8 2104.05   205.2 2103.46   214.9 2103.57   224.7  2105.1   234.5 2108.54
   244.2 2112.76     254 2116.86   263.8 2120.65   293.1 2131.57
#Mann= 3 , 0 , 0
       0      .1       0   108.5    .045       0     127      .1       0
#XS Ineff= 2 , 0
                          156.34         2104.68
Permanent Ineff=
       F       F
Bank Sta=108.5,127
XS Rating Curve= 0 ,0
Exp/Cntr=0.3,0.1

Type RM Length L Ch R = 1 ,24179.8 ,841.9,825.7,804.1
XS GIS Cut Line= 3
     1948885.771      361278.558     1948770.079      361657.126
     1948784.208      361861.892
#Sta/Elev= 30
       0 2139.61     9.6 2138.47    19.3  2136.8    38.6 2132.02    67.6 2123.77
   106.2 2114.51   125.5 2110.55   135.2 2109.24   144.8 2108.97   154.5 2108.17
   164.1 2105.99   173.8 2102.95   183.4 2100.44   193.1 2099.36   202.8 2098.91
   270.3 2095.99   334.3 2093.68   366.9 2092.41   376.5 2094.43   386.2 2100.78
   395.8 2109.76   405.6  2117.5   415.4 2123.45     435 2133.26   444.7 2137.78
   454.5 2141.73   464.3 2144.85     474 2147.11   581.6  2165.8   601.1 2169.99
#Mann= 3 , 0 , 0
       0      .1       0   334.3    .045       0   376.5      .1       0
Bank Sta=334.3,376.5
XS Rating Curve= 0 ,0
Exp/Cntr=0.3,0.1

Type RM Length L Ch R = 1 ,23354   ,405.5,404.9,403.8
XS GIS Cut Line= 2
     1947982.125        361554.6     1948247.518      362039.561
#Sta/Elev= 30
       0 2089.25     9.7    2088    19.4 2087.38    29.1 2087.29    38.8 2087.54
    67.9 2088.77    77.6 2088.59    87.3 2087.96   106.7 2086.35   145.5 2082.92
   155.2 2082.16   174.6 2080.89   281.3 2076.04   325.5  2074.3   339.5 2074.01
   340.5 2074.02   349.2 2074.14   368.6 2074.74   378.2 2076.94     388 2083.14
   407.4  2100.1     417 2108.26   426.8 2116.27   436.4  2124.3   446.1  2131.6
   455.8 2137.28   475.2 2146.82   494.6 2156.93   504.3  2162.1   552.8  2188.6
#Mann= 3 , 0 , 0
       0      .1       0   325.5    .045       0   340.5      .1       0
Bank Sta=325.5,340.5
XS Rating Curve= 0 ,0
Exp/Cntr=0.3,0.1

Type RM Length L Ch R = 1 ,22949.1 ,708.6,695.6,682.5
XS GIS Cut Line= 2
     1947593.872      361640.255     1947889.011       362174.11
#Sta/Elev= 30
       0 2126.46    39.4 2111.25    49.2  2107.1      59 2102.12    78.7 2090.37
    88.6  2086.1    98.4 2083.93   157.4 2079.86   177.1 2077.22   196.8 2073.67
   206.6 2072.44   216.4 2071.75   344.4 2068.67   354.2 2068.12     364 2067.03
   373.9 2065.76   383.7 2065.56   393.6 2065.58   403.4 2065.68   413.2 2066.64
   423.1 2069.68   442.8 2079.67   501.8  2114.7   511.6 2120.22   521.5 2125.21
   531.3 2129.65     551 2137.47   560.8 2141.78   590.3 2156.31     610  2167.5
#Mann= 3 , 0 , 0
       0      .1       0     364    .045       0   393.6      .1       0
Bank Sta=364,393.6
XS Rating Curve= 0 ,0
Exp/Cntr=0.3,0.1

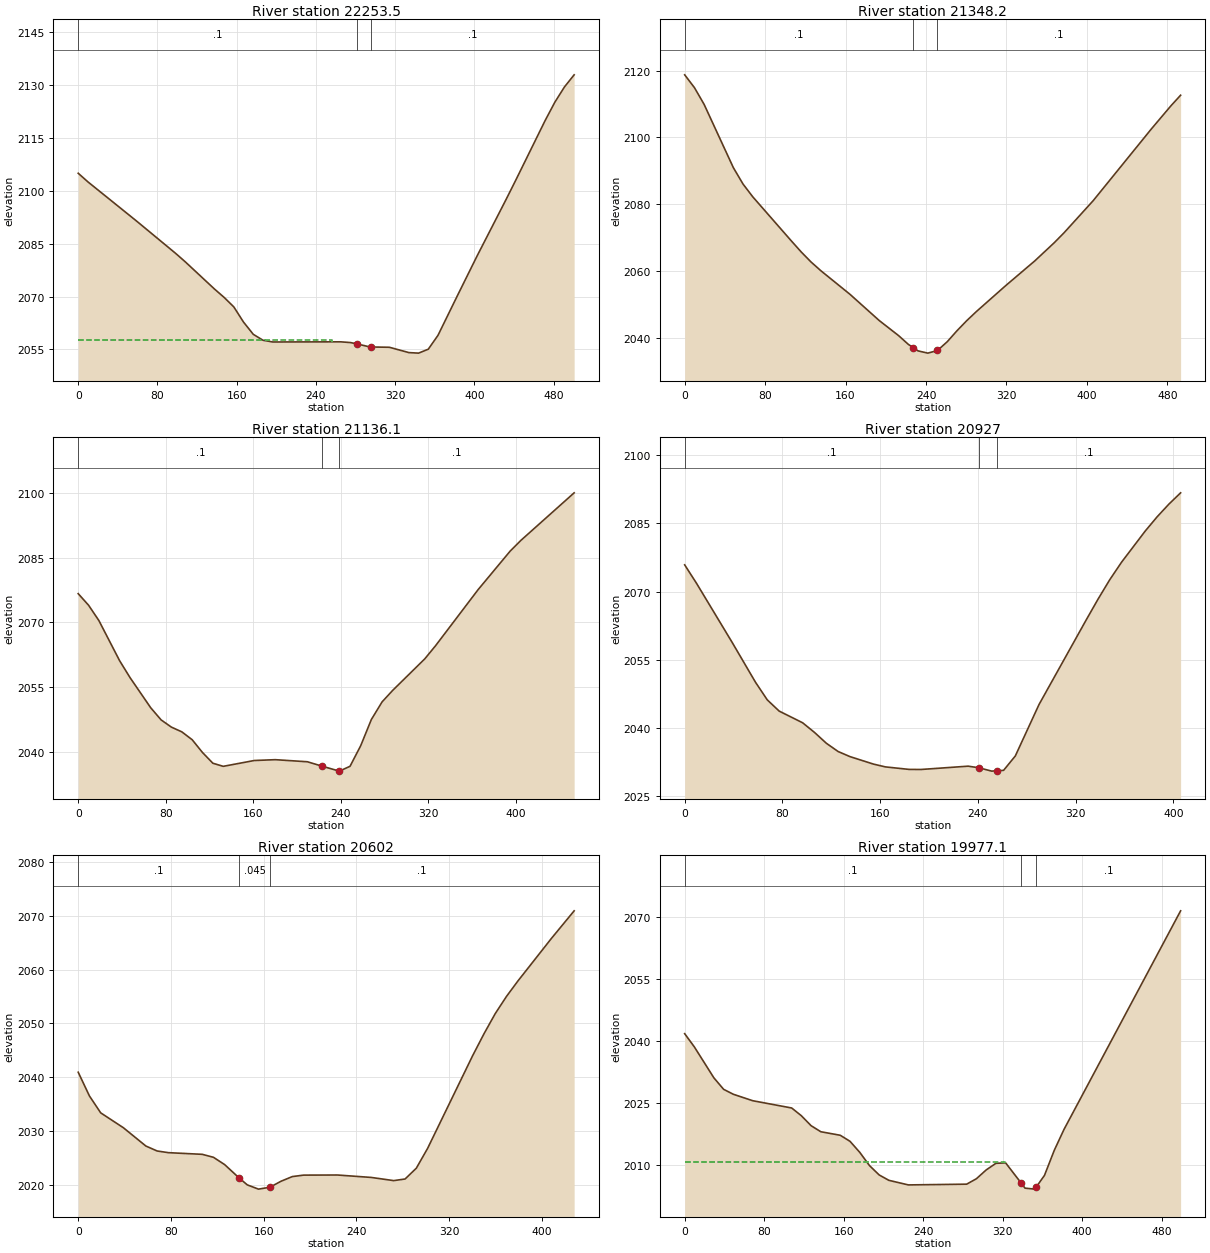
Type RM Length L Ch R = 1 ,22253.5 ,906.4,905.3,904.3
XS GIS Cut Line= 2
     1947114.706       362330.36     1947564.358      362550.846
#Sta/Elev= 30
       0 2104.93     9.8 2102.49    58.9 2091.39    98.2 2082.27     108 2079.86
   137.5 2072.15   147.3 2069.76   157.1 2067.07   166.9 2062.77   176.8 2059.28
   186.6 2057.61   196.4 2057.12   265.1 2057.16     275 2056.95   281.1  2056.6
   294.6 2055.71   296.1  2055.7   314.2 2055.62   333.9 2054.11   343.7 2053.96
   353.5 2055.07   363.3    2059     383 2070.29   402.6 2081.39   432.1 2097.52
   441.9    2103   471.3 2119.75   481.2 2125.01     491 2129.38   500.8 2132.82
#Mann= 3 , 0 , 0
       0      .1       0   281.1    .045       0   296.1      .1       0
#XS Ineff= 2 , 0
          256.06 2057.79
Permanent Ineff=
       F       F
Bank Sta=281.1,296.1
XS Rating Curve= 0 ,0
Exp/Cntr=0.3,0.1

Type RM Length L Ch R = 1 ,21348.2 ,209.4,212.1,214.7
XS GIS Cut Line= 2
     1946906.372      363189.735     1947353.421      363398.068
#Sta/Elev= 30
       0 2118.74     9.7 2114.91    19.3 2109.91    48.4 2090.95      58 2086.05
    67.7 2082.22   106.4  2068.9     116 2065.67   125.7 2062.69   135.4 2060.09
   164.4 2053.02   193.4 2045.19   212.8 2040.64   222.4 2038.04   227.4 2037.03
   232.1 2036.08   241.8 2035.41   251.4  2036.2   261.1 2038.82   270.8 2042.11
   280.4  2045.1   290.1 2047.86   319.1 2055.58   348.2 2063.03   367.5 2068.46
   377.2 2071.42   406.2 2081.04   464.2 2102.57   483.5 2109.44   493.2 2112.64
#Mann= 3 , 0 , 0
       0      .1       0   227.4    .045       0   251.4      .1       0
Bank Sta=227.4,251.4
XS Rating Curve= 0 ,0
Exp/Cntr=0.3,0.1

Type RM Length L Ch R = 1 ,21136.1 ,184,209,234.1
XS GIS Cut Line= 3
     1946922.041      363293.429     1946984.976      363451.849
     1947225.758      363600.427
#Sta/Elev= 30
       0 2076.65     9.5 2073.96    18.9 2070.42    37.9  2061.1    47.4  2057.2
    66.3 2050.22    75.8 2047.41    85.2 2045.74    94.7 2044.65   104.2 2042.82
   113.6 2039.87   123.1 2037.38   132.6 2036.66     161 2038.01   180.2  2038.2
   209.5 2037.72   223.2 2036.68   238.2 2035.59   238.8 2035.55   248.5 2036.67
   258.3 2041.46     268  2047.5   277.8 2051.58   287.5 2054.25   316.8 2061.54
   326.6 2064.56   365.6 2077.58   394.9  2086.5   404.6 2088.96   453.4    2100
#Mann= 3 , 0 , 0
       0      .1       0   223.2    .045       0   238.2      .1       0
Bank Sta=223.2,238.2
XS Rating Curve= 0 ,0
Exp/Cntr=0.3,0.1

Type RM Length L Ch R = 1 ,20927   ,326.6,325,323.3
XS GIS Cut Line= 2
     1946884.671      363302.582     1946850.817      363707.096
#Sta/Elev= 30
       0 2075.86     9.7  2071.8    38.7 2058.88      58 2050.03    67.6 2046.17
    77.3 2043.71    96.6 2041.12   106.3    2039     116 2036.62   125.6 2034.81
   135.3 2033.69   154.6 2032.04   164.3 2031.43   183.6 2030.88   193.3 2030.86
     232 2031.59   240.8 2031.24   251.3  2030.5   255.8 2030.58     261 2030.67
   270.6 2033.83     290 2045.14   328.6 2063.74   338.3 2068.31   347.9 2072.59
   357.6 2076.46   376.9 2083.28   386.6  2086.4   396.3 2089.21   405.9  2091.7
#Mann= 3 , 0 , 0
       0      .1       0   240.8    .045       0   255.8      .1       0
Bank Sta=240.8,255.8
XS Rating Curve= 0 ,0
Exp/Cntr=0.3,0.1

Type RM Length L Ch R = 1 ,20602   ,625.2,624.9,624.5
XS GIS Cut Line= 2
     1946548.733        363334.7     1946546.129      363762.651
#Sta/Elev= 30
       0 2040.94     9.7 2036.53    19.4  2033.4    38.9 2030.65    58.4 2027.24
    68.1 2026.32    77.8 2026.01     107  2025.7   116.7 2025.15   126.4 2023.79
   138.9 2021.31   145.9 2020.03   155.6 2019.24   165.4 2019.59   175.1 2020.71
   184.8 2021.57   194.5 2021.84   223.7 2021.86   252.9 2021.41   272.3 2020.82
   282.1 2021.12   291.8 2023.13   301.5 2026.79   340.4 2044.01   350.2 2048.08
   359.9 2051.82   369.6 2055.01   379.3 2057.83   408.5 2065.81     428  2070.9
#Mann= 3 , 0 , 0
       0      .1       0   138.9    .045       0   165.4      .1       0
Bank Sta=138.9,165.4
XS Rating Curve= 0 ,0
Exp/Cntr=0.3,0.1

Type RM Length L Ch R = 1 ,19977.1 ,728.9,715.9,702.9
XS GIS Cut Line= 2
     1945967.148      363268.108     1945967.148       363767.24
#Sta/Elev= 30
       0 2041.71     9.8 2038.48    29.4 2031.01    39.2 2028.23    48.9 2027.04
    68.5 2025.47   107.7 2023.71   117.4 2021.84   127.2 2019.43     137 2017.96
   156.6  2017.1   166.4 2015.64   176.2 2012.97     186 2009.76   195.7  2007.5
   205.5 2006.19   225.1 2005.08   283.8 2005.26   293.6 2006.58   303.4  2008.7
   313.2 2010.31     323 2010.42   338.8 2005.48   342.5  2004.3   352.3 2004.06
   353.8 2004.57   362.1 2007.39   371.9 2013.43   381.7  2018.5   499.1 2071.46
#Mann= 3 , 0 , 0
       0      .1       0   338.8    .045       0   353.8      .1       0
#XS Ineff= 2 , 0
          322.54  2010.7
Permanent Ineff=
       F       F
Bank Sta=338.8,353.8
XS Rating Curve= 0 ,0
Exp/Cntr=0.3,0.1

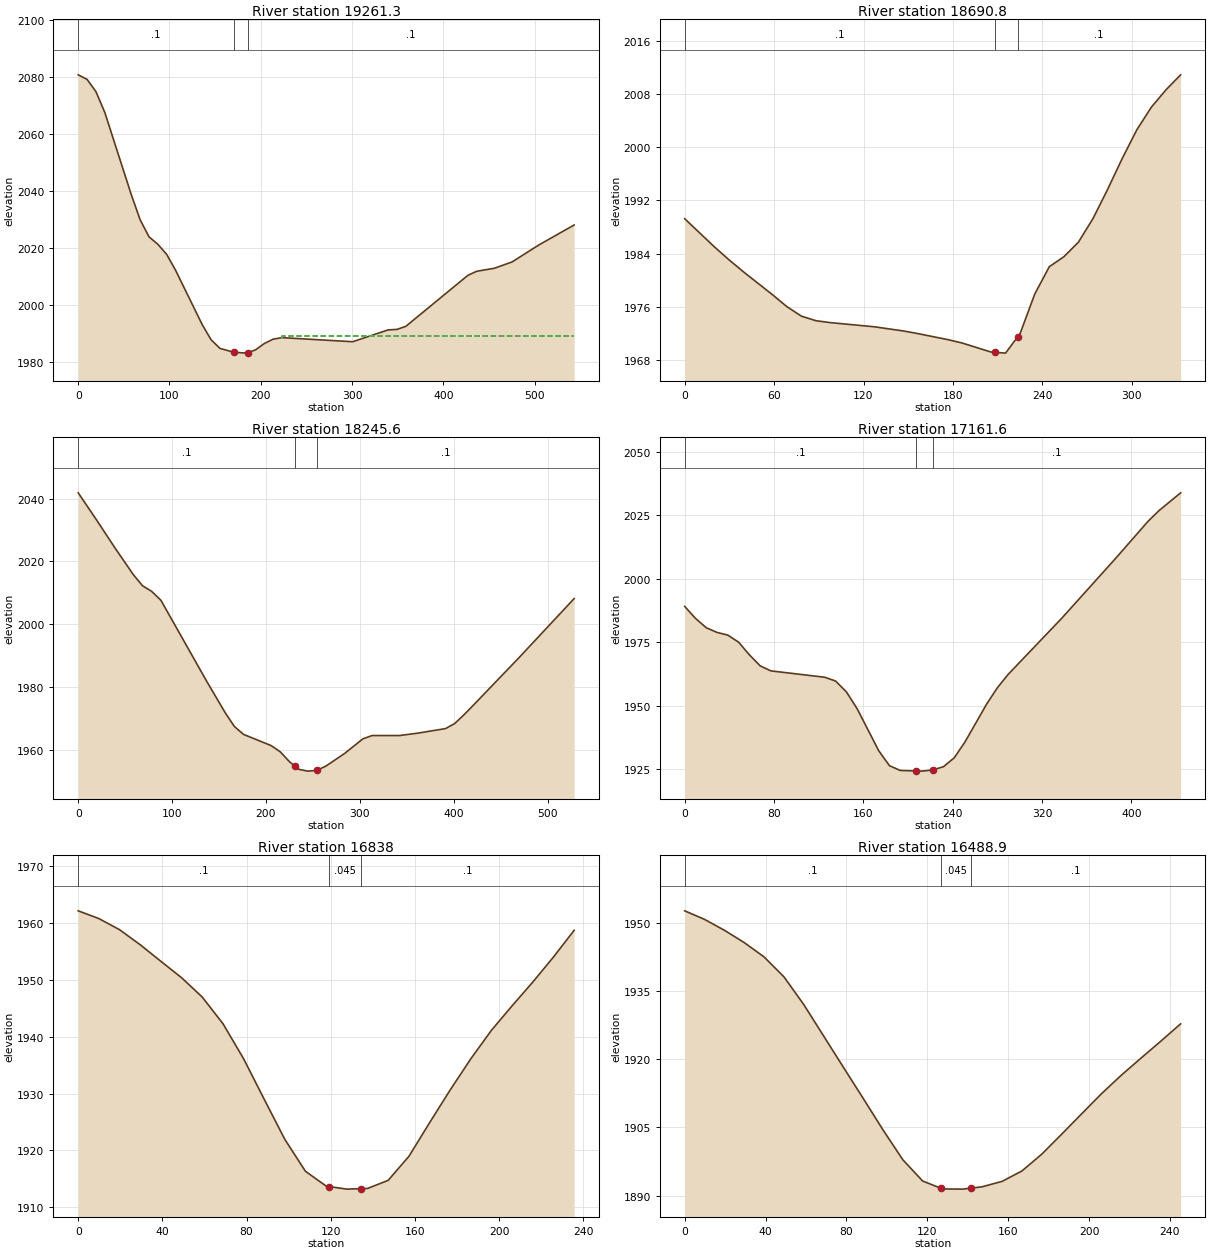
Type RM Length L Ch R = 1 ,19261.3 ,564.5,570.5,576.4
XS GIS Cut Line= 2
     1945174.601      363467.512     1945470.608      363923.241
#Sta/Elev= 30
       0  2080.7     9.7 2079.11    19.4 2074.82    29.1 2067.54    58.2 2038.63
    67.9 2029.84    77.6 2023.88    87.3 2021.27      97  2017.7   106.7 2012.16
   135.9 1993.07   145.6 1987.79   155.3 1984.76   170.6  1983.4   184.4  1983.1
   185.6 1983.24   194.1 1984.21   203.8 1986.44   213.5 1987.99   223.2 1988.53
   300.8  1987.1   339.6 1991.25   349.3 1991.42     359  1992.5     427 2010.39
   436.7 2011.81   456.1 2012.87   475.5  2015.1   504.6 2021.01   543.4 2028.04
#Mann= 3 , 0 , 0
       0      .1       0   170.6    .045       0   185.6      .1       0
#XS Ineff= 2 , 0
                           223.1         1988.94
Permanent Ineff=
       F       F
Bank Sta=170.6,185.6
XS Rating Curve= 0 ,0
Exp/Cntr=0.3,0.1

Type RM Length L Ch R = 1 ,18690.8 ,439,445.1,450.9
XS GIS Cut Line= 2
     1944824.573        363804.6     1944923.531      364122.308
#Sta/Elev= 30
       0 1989.23    19.6 1985.07    29.4 1983.12    39.2 1981.29    58.7 1977.85
    68.5 1976.03    78.3 1974.59    88.1  1973.9    97.9 1973.61   127.2 1972.99
   146.8 1972.36   156.6 1971.96   176.2 1971.08     186 1970.56   205.5  1969.2
   208.4 1969.15   215.3 1969.03   223.4 1971.46   225.1 1971.97   234.9  1977.9
   244.7 1982.02   254.5 1983.52   264.2  1985.7     274 1989.25   283.8 1993.63
   293.6 1998.27   303.4 2002.58   313.2    2006     323  2008.6   332.8 2010.85
#Mann= 3 , 0 , 0
       0      .1       0   208.4    .045       0   223.4      .1       0
Bank Sta=208.4,223.4
XS Rating Curve= 0 ,0
Exp/Cntr=0.3,0.1

Type RM Length L Ch R = 1 ,18245.6 ,1091.7,1084,1076.3
XS GIS Cut Line= 2
     1944436.754      363788.693     1944457.588      364316.471
#Sta/Elev= 30
       0 2041.82    19.6 2033.16    39.1 2024.29    58.7 2015.75    68.5 2012.22
    78.2 2010.42      88 2007.62   136.9 1981.74   156.5 1971.78   166.3 1967.38
   176.1 1964.84   205.4 1961.29   215.2 1959.29     225 1956.14   230.6 1954.76
   234.8 1953.73   244.5 1953.14   254.3 1953.37   264.1  1954.8   283.7 1958.76
   303.2 1963.43     313 1964.48   342.3 1964.48   361.9 1965.25   391.2 1966.69
     401 1968.31   410.8 1971.07   420.6 1974.07   469.5  1989.3   528.2 2008.13
#Mann= 3 , 0 , 0
       0      .1       0   230.6    .045       0   254.3      .1       0
Bank Sta=230.6,254.3
XS Rating Curve= 0 ,0
Exp/Cntr=0.3,0.1

Type RM Length L Ch R = 1 ,17161.6 ,316.1,323.6,331.1
XS GIS Cut Line= 2
     1943408.108      364270.464     1943573.039       364682.79
#Sta/Elev= 30
       0 1989.19     9.6 1984.51    19.3  1980.8      29 1978.94    38.6 1977.89
    48.3 1975.11    57.9 1970.15    67.6 1965.78    77.2  1963.8   125.5 1961.29
   135.2 1959.78   144.8 1955.55   154.5 1948.86   173.8 1932.34   183.4 1926.47
   193.1 1924.59   207.1  1924.4   212.4 1924.33   222.1 1924.79   231.7 1926.07
   241.4 1929.58     251 1935.81   270.3 1950.65     280 1957.15   289.6 1962.39
   337.9 1984.64   386.2 2008.25   415.1 2022.78   424.8 2026.92   444.1 2033.91
#Mann= 3 , 0 , 0
       0      .1       0   207.1    .045       0   222.1      .1       0
Bank Sta=207.1,222.1
XS Rating Curve= 0 ,0
Exp/Cntr=0.3,0.1

Type RM Length L Ch R = 1 ,16838   ,349.2,349.1,348.9
XS GIS Cut Line= 2
     1943180.039      364453.587     1943191.433      364689.056
#Sta/Elev= 27
       0 1962.19     9.8 1960.83    19.6 1958.88    29.5 1956.21    39.3  1953.3
    49.1 1950.42    58.9 1947.03    68.8 1942.32    78.6 1936.15    88.4 1929.01
    98.2 1921.95     108 1916.33   117.9 1913.71   119.4 1913.63   127.7 1913.19
   134.4 1913.27   137.5 1913.31   147.3 1914.73   157.2 1918.98     167 1924.88
   176.8 1930.66   186.6 1936.14   196.4 1941.16   206.3  1945.5   216.1 1949.67
   225.9 1954.07   235.7 1958.76
#Mann= 3 , 0 , 0
       0      .1       0   119.4    .045       0   134.4      .1       0
Bank Sta=119.4,134.4
XS Rating Curve= 0 ,0
Exp/Cntr=0.3,0.1

Type RM Length L Ch R = 1 ,16488.9 ,660.7,659.7,658.7
XS GIS Cut Line= 2
     1942832.588      364451.887     1942848.213      364696.679
#Sta/Elev= 28
       0 1952.72     9.8 1950.84    19.6 1948.45    29.4 1945.74    39.2 1942.59
    49.1 1938.18    58.9 1932.08    68.7 1925.17    78.5 1918.26    88.3  1911.4
    98.1 1904.46   107.9 1897.88   117.7  1893.2   126.8 1891.59   127.6 1891.45
   137.4 1891.41   141.8 1891.64   147.2 1891.93     157 1893.12   166.8 1895.41
   176.6  1899.1   186.4 1903.48   196.2 1907.93     206 1912.36   215.9 1916.48
   225.7 1920.27   235.5    1924   245.3 1927.82
#Mann= 3 , 0 , 0
       0      .1       0   126.8    .045       0   141.8      .1       0
Bank Sta=126.8,141.8
XS Rating Curve= 0 ,0
Exp/Cntr=0.3,0.1

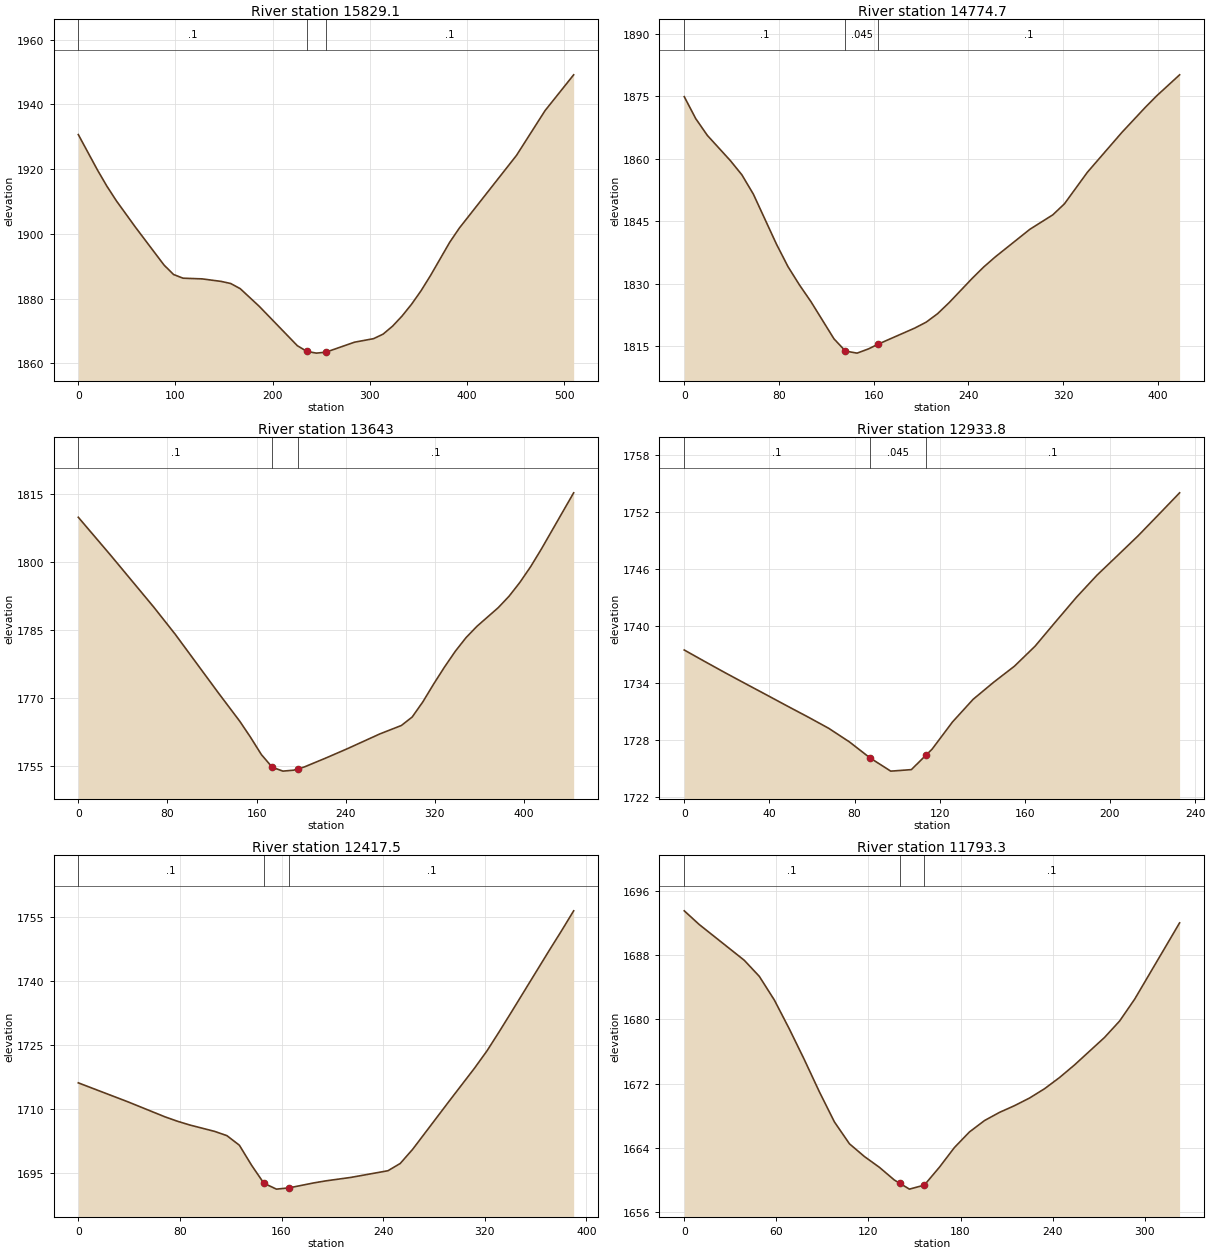
Type RM Length L Ch R = 1 ,15829.1 ,1054.5,1054.4,1054.1
XS GIS Cut Line= 2
     1942210.192      364504.839     1942253.594      365012.651
#Sta/Elev= 30
       0 1930.69    19.6  1919.8    29.4 1914.75    39.2 1910.21    58.8 1902.06
    88.2 1890.37      98 1887.44   107.8  1886.3   127.4 1886.09     147 1885.31
   156.8 1884.66   166.6 1883.07   186.2  1877.6   225.4 1865.43   235.2 1863.68
     245 1863.14   254.8 1863.44   284.2 1866.52   303.8 1867.61   313.6 1869.01
   323.4 1871.48   333.2 1874.63     343 1878.29   352.8 1882.48   362.6 1887.22
   382.2 1897.42     392 1901.76   450.9 1924.27   480.3 1938.11   509.7 1949.16
#Mann= 3 , 0 , 0
       0      .1       0   235.2    .045       0   254.8      .1       0
Bank Sta=235.2,254.8
XS Rating Curve= 0 ,0
Exp/Cntr=0.3,0.1

Type RM Length L Ch R = 1 ,14774.7 ,1125.8,1131.7,1137.3
XS GIS Cut Line= 2
     1941177.206      364700.151     1941216.268      365116.818
#Sta/Elev= 30
       0 1874.93     9.7 1869.66    19.5 1865.64    38.9  1859.6    48.7 1856.17
    58.4 1851.53    77.9 1839.54    87.6 1834.16    97.3 1829.76   107.1 1825.71
   126.5 1816.81   136.2 1813.87     146 1813.38   155.7  1814.4   163.7 1815.52
   194.6 1819.37   204.4 1820.81   214.1 1822.86   223.8  1825.5   243.3 1831.33
     253 1834.05   262.8 1836.48     292  1843.1   311.4 1846.57   321.2 1849.21
   340.6 1856.79   369.8 1866.37   389.3  1872.3     399 1875.09   418.5 1880.17
#Mann= 3 , 0 , 0
       0      .1       0   136.2    .045       0   163.7      .1       0
Bank Sta=136.2,163.7
XS Rating Curve= 0 ,0
Exp/Cntr=0.3,0.1

Type RM Length L Ch R = 1 ,13643   ,715.5,709.2,702.6
XS GIS Cut Line= 2
     1940170.261      364465.776     1940096.476      364904.144
#Sta/Elev= 30
       0 1809.94      29 1801.56    67.6 1790.13      87 1784.09   125.6 1771.18
     145 1764.85   154.6 1761.33   164.3 1757.52     174 1754.73   183.6 1753.87
   193.3 1754.08     197 1754.36   202.9  1754.8   222.3 1756.78   241.6 1758.84
   270.6 1762.09   289.9 1763.95   299.6 1765.82   309.2 1769.18   318.9 1773.12
   328.6 1776.86   338.2 1780.31   347.9 1783.35   357.6 1785.83   376.9 1789.99
   386.6 1792.52   396.2 1795.54   405.9 1799.03   415.5 1802.91   444.5 1815.34
#Mann= 3 , 0 , 0
       0      .1       0     174    .045       0     197      .1       0
Bank Sta=174,197
XS Rating Curve= 0 ,0
Exp/Cntr=0.3,0.1

Type RM Length L Ch R = 1 ,12933.8 ,517.7,516.3,514.9
XS GIS Cut Line= 2
     1939457.588      364532.616     1939478.421      364764.387
#Sta/Elev= 27
       0 1737.47     9.7 1736.25    19.4 1735.05    29.1 1733.88    38.8 1732.72
    48.5 1731.55    58.2  1730.4    67.9 1729.21    77.6 1727.78    87.3 1726.09
      97  1724.7    98.4 1724.72   106.7 1724.86   113.4 1726.35   116.4 1727.01
     126 1729.88   135.7 1732.27   145.4 1734.08   155.1 1735.76   164.8 1737.87
   174.5 1740.46   184.2 1743.02   193.9 1745.36   203.6 1747.44   213.3 1749.53
     223 1751.78   232.7 1754.04
#Mann= 3 , 0 , 0
       0      .1       0    87.3    .045       0   113.4      .1       0
Bank Sta=87.3,113.4
XS Rating Curve= 0 ,0
Exp/Cntr=0.3,0.1

Type RM Length L Ch R = 1 ,12417.5 ,614.3,624.2,631.6
XS GIS Cut Line= 2
     1938954.983      364579.491     1939014.879      364964.908
#Sta/Elev= 26
       0 1716.12      39 1711.68    68.3 1708.15      78 1707.13    87.8 1706.24
   107.3 1704.75     117 1703.75   126.8 1701.51   136.5 1696.78   146.1  1692.6
     156 1691.22   165.8 1691.51   185.3 1692.67     195 1693.16   214.5 1693.96
   243.8 1695.53   253.5 1697.24   263.3 1700.57   292.5 1712.03     312 1719.58
   321.8 1723.63   331.5 1728.15   341.3 1732.85   370.5 1747.01   380.3 1751.67
     390 1756.42
#Mann= 3 , 0 , 0
       0      .1       0   146.1    .045       0   165.8      .1       0
Bank Sta=146.1,165.8
XS Rating Curve= 0 ,0
Exp/Cntr=0.3,0.1

Type RM Length L Ch R = 1 ,11793.3 ,615.4,631.2,646.9
XS GIS Cut Line= 2
     1938540.921      364532.616     1938501.858      364852.929
#Sta/Elev= 30
       0 1693.52     9.8 1691.81    39.1 1687.36    48.9 1685.36    58.7 1682.41
    68.4 1678.83    78.2    1675      88 1670.99    97.8 1667.24   107.6 1664.51
   117.3 1662.93   127.1 1661.58   136.9 1659.99   140.3  1659.6   146.7 1658.86
   156.4 1659.36   166.2 1661.58     176 1664.04   185.8 1665.98   195.6  1667.4
   205.4 1668.42   215.1 1669.25   224.9  1670.2   234.7 1671.36   244.5 1672.76
   254.2 1674.32   273.8 1677.75   283.6 1679.79   293.4 1682.51   322.7 1692.02
#Mann= 3 , 0 , 0
       0      .1       0   140.3    .045       0   156.4      .1       0
Bank Sta=140.3,156.4
XS Rating Curve= 0 ,0
Exp/Cntr=0.3,0.1

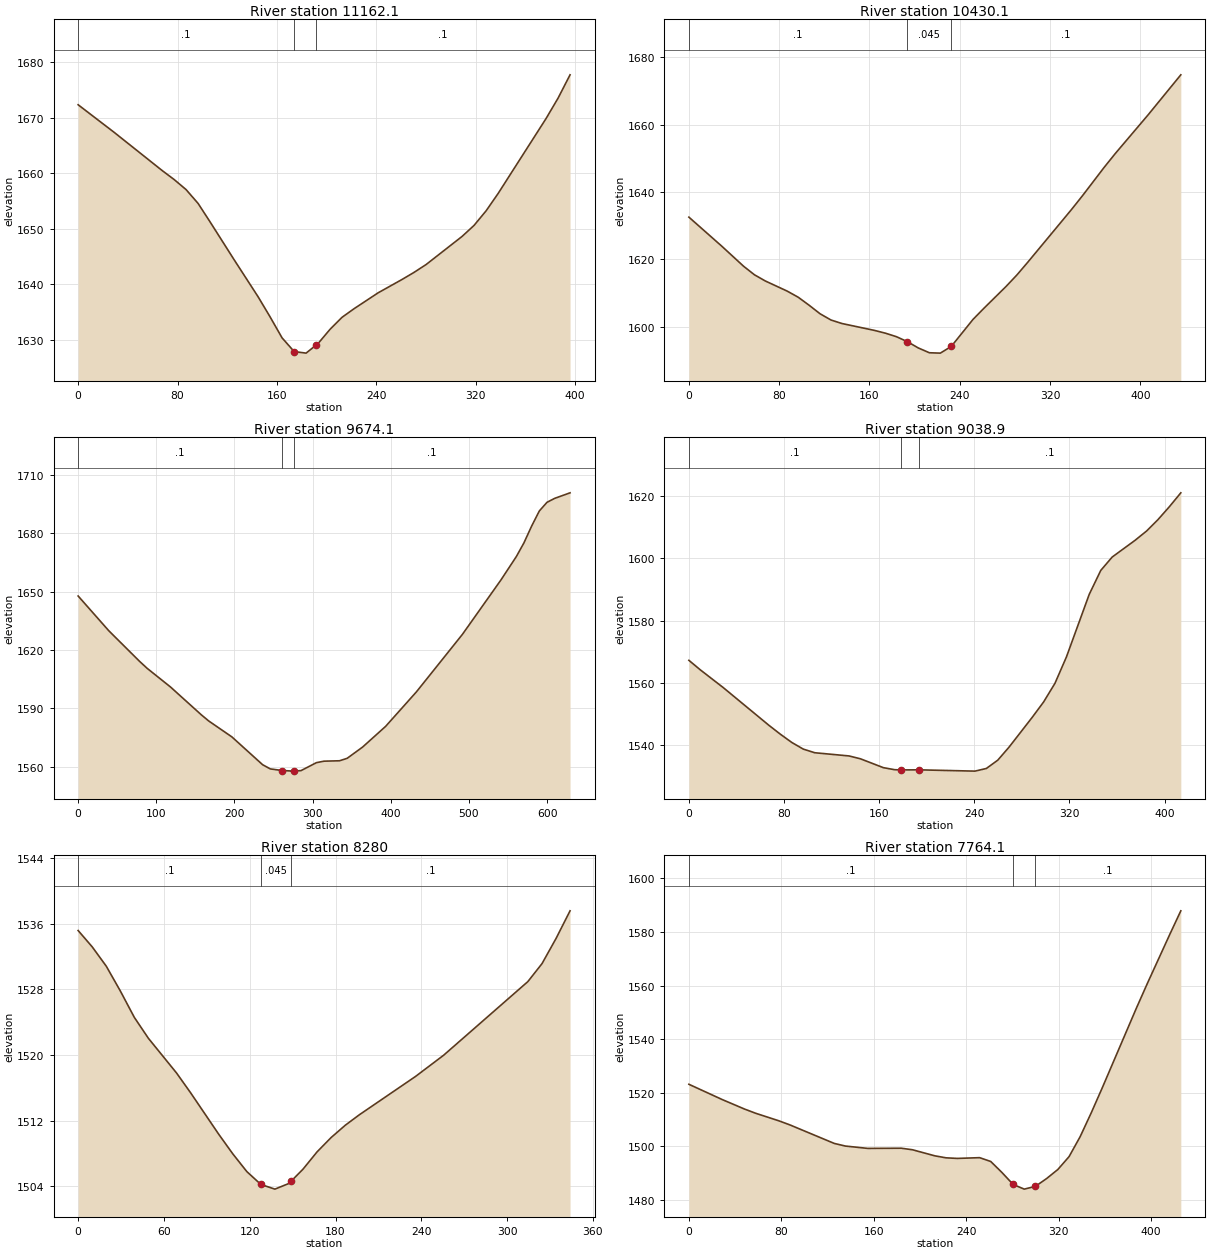
Type RM Length L Ch R = 1 ,11162.1 ,720.4,732.1,743.7
XS GIS Cut Line= 2
     1938065.226      364352.929     1937778.768      364626.366
#Sta/Elev= 29
       0 1672.31      29 1667.34    67.6 1660.47    77.3 1658.84    86.9 1657.03
    96.6 1654.53   106.2 1651.22   125.6 1644.39   144.9 1637.72   154.5 1634.12
   164.2 1630.32   173.9 1627.86   183.5 1627.58   191.6 1629.03   193.2 1629.32
   202.8 1631.87   212.5 1634.04   222.2 1635.59   241.5 1638.44   260.8 1640.85
   270.4 1642.12   280.1 1643.53   309.1  1648.6   318.7 1650.58   328.4  1653.2
   338.1 1656.33   376.7 1669.83   386.4 1673.52     396  1677.7
#Mann= 3 , 0 , 0
       0      .1       0   173.9    .045       0   191.6      .1       0
Bank Sta=173.9,191.6
XS Rating Curve= 0 ,0
Exp/Cntr=0.3,0.1

Type RM Length L Ch R = 1 ,10430.1 ,761.4,756,750.4
XS GIS Cut Line= 2
     1937713.664      363853.797     1937292.657      363966.644
#Sta/Elev= 30
       0 1632.52    29.1  1623.9    48.4 1617.95    58.1 1615.39    67.8 1613.54
    87.2 1610.53    96.9 1608.72   106.6 1606.33   116.2 1603.82   125.9 1601.96
   135.6 1600.92   164.7 1598.85   174.4 1598.02     184 1596.99   193.7 1595.51
   203.2 1593.67   213.1 1592.23   222.8 1592.12   232.5 1594.11   251.8 1602.15
   261.5 1605.47   280.9 1611.88   290.6 1615.32   300.3 1619.13     339 1634.77
   348.7 1638.85   368.1 1647.36   377.8  1651.4   406.8 1662.86   435.9  1674.8
#Mann= 3 , 0 , 0
       0      .1       0   193.7    .045       0   232.5      .1       0
Bank Sta=193.7,232.5
XS Rating Curve= 0 ,0
Exp/Cntr=0.3,0.1

Type RM Length L Ch R = 1 ,9674.1  ,648.3,635.2,622.2
XS GIS Cut Line= 2
     1937561.754      363059.526     1937010.539      363363.346
#Sta/Elev= 30
       0 1647.69    39.3  1629.8    78.7 1614.07    88.5 1610.45     118 1600.99
   157.4  1586.7   167.2 1583.43   196.7 1575.28     236 1560.99   245.9 1558.82
     261    1558   275.4 1557.68     276  1557.7   285.2 1557.95   304.9 1562.03
   314.7  1562.8   334.4    1563   344.2 1564.26   363.9 1570.02   393.4 1580.67
   432.7 1598.36   491.7 1627.98   540.9 1655.89   560.6 1667.91   570.4    1675
   580.2 1683.58   590.1  1691.4   599.9 1695.84   609.7 1697.87   629.4 1700.72
#Mann= 3 , 0 , 0
       0      .1       0     261    .045       0     276      .1       0
Bank Sta=261,276
XS Rating Curve= 0 ,0
Exp/Cntr=0.3,0.1

Type RM Length L Ch R = 1 ,9038.9  ,758.8,758.9,758.9
XS GIS Cut Line= 2
     1937014.879      362638.519     1936819.567      363003.103
#Sta/Elev= 30
       0 1567.28     9.6 1564.23    28.9 1558.54    67.3 1546.46      77 1543.59
    86.6 1540.95    96.2 1538.84   105.8 1537.68   134.7 1536.65   144.3 1535.73
   163.5  1532.9   173.1 1532.24   178.7 1532.18   193.7  1532.2   240.5 1531.79
   250.1 1532.64   259.7  1535.3   269.3 1539.53   288.6 1548.99   298.2 1553.92
   307.8 1559.93   317.4 1568.34   336.6 1588.41   346.3 1596.08   355.9 1600.36
   375.1 1605.71   384.8 1608.69   394.4 1612.35     404 1616.49   413.6 1620.93
#Mann= 3 , 0 , 0
       0      .1       0   178.7    .045       0   193.7      .1       0
Bank Sta=178.7,193.7
XS Rating Curve= 0 ,0
Exp/Cntr=0.3,0.1

Type RM Length L Ch R = 1 ,8280    ,492.4,515.8,539.3
XS GIS Cut Line= 2
     1936320.435      362382.443     1936151.164      362681.922
#Sta/Elev= 26
       0 1535.16     9.8 1533.18    19.7 1530.81    29.5  1527.8    39.3 1524.58
    49.1 1522.04    68.8 1517.81    78.6 1515.41    98.3 1510.35   108.1 1507.97
     118 1505.79   127.8 1504.23   137.6 1503.66   147.4 1504.35   148.8  1504.6
   157.3  1506.1   167.1  1508.2   176.9 1509.94   186.8 1511.44   196.6 1512.71
   235.9 1517.38   255.6 1519.97   314.5 1528.94   324.4 1531.13   334.2 1534.19
     344 1537.56
#Mann= 3 , 0 , 0
       0      .1       0   127.8    .045       0   148.8      .1       0
Bank Sta=127.8,148.8
XS Rating Curve= 0 ,0
Exp/Cntr=0.3,0.1

Type RM Length L Ch R = 1 ,7764.1  ,365.6,373.5,381.4
XS GIS Cut Line= 2
     1936112.101      362217.512     1935686.754      362234.873
#Sta/Elev= 30
       0 1523.14      29  1517.4    48.4 1513.84      58 1512.28    77.4 1509.56
    87.1 1508.02   125.8 1501.05   135.4 1500.07   154.8 1499.19   183.8 1499.26
   193.5 1498.68   212.8 1496.42   222.5 1495.67   232.2 1495.45   251.6 1495.73
   261.2 1494.31   270.9  1490.2   280.6 1485.72   290.2 1483.98   299.9 1485.02
   309.6 1487.94   319.3 1491.32     329 1496.12   338.6 1503.58   348.3 1512.59
     358 1522.09     387 1551.32   396.7 1560.76     416 1578.97   425.7 1587.92
#Mann= 3 , 0 , 0
       0      .1       0   280.6    .045       0   299.9      .1       0
Bank Sta=280.6,299.9
XS Rating Curve= 0 ,0
Exp/Cntr=0.3,0.1

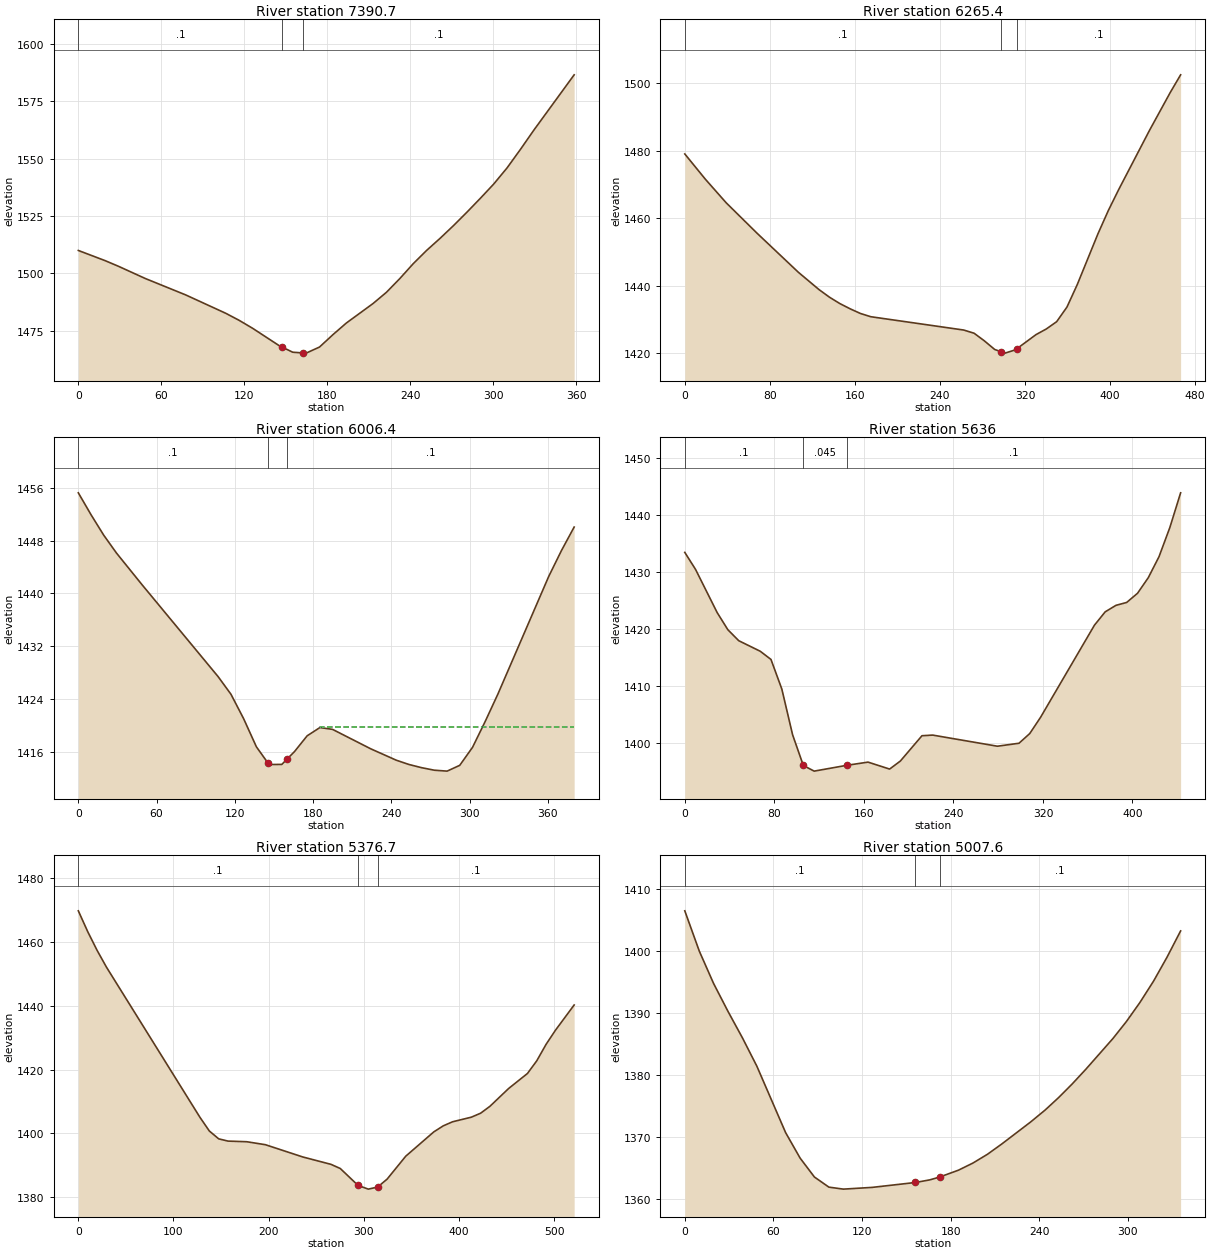
Type RM Length L Ch R = 1 ,7390.7  ,1130.6,1125.3,1119.5
XS GIS Cut Line= 2
     1936133.167      361946.527     1935790.921      361839.908
#Sta/Elev= 30
       0 1509.92    19.4 1505.47    29.1 1502.99    48.4 1497.69    77.5 1490.56
   106.6 1482.51   116.3 1479.43     126 1475.97   145.3 1468.36   147.4 1467.75
     155 1465.53   162.4 1465.22   164.7 1465.13   174.4 1467.79   184.1 1473.19
   193.8 1478.27   213.1 1486.77   222.8 1491.68   232.5 1497.69   242.2 1504.18
   251.9 1509.98   261.6 1515.23   271.3 1520.78     281 1526.63   290.6 1532.62
   300.3 1538.87     310 1545.94   319.7 1554.04   329.4 1562.45   358.5 1586.54
#Mann= 3 , 0 , 0
       0      .1       0   147.4    .045       0   162.4      .1       0
Bank Sta=147.4,162.4
XS Rating Curve= 0 ,0
Exp/Cntr=0.3,0.1

Type RM Length L Ch R = 1 ,6265.4  ,262.5,259,255.5
XS GIS Cut Line= 2
      1936247.75      360865.798      1935782.24      360837.304
#Sta/Elev= 30
       0 1478.99    19.4  1471.5    38.9 1464.56      68 1455.54   106.9 1443.98
   126.3 1438.87     136 1436.65   145.7 1434.77   155.5  1433.2   165.2 1431.82
   174.9 1430.86   262.3 1426.92   272.1 1425.98   281.8 1423.72   291.5 1421.17
   297.1 1420.55   301.2 1420.09   310.9 1421.05   312.1 1421.33   330.4 1425.57
   340.1 1427.24   349.8 1429.39   359.5 1433.72   369.2 1440.38   388.6 1455.35
   398.4 1462.26   408.1 1468.43   437.2 1486.01   456.7  1497.2   466.4 1502.39
#Mann= 3 , 0 , 0
       0      .1       0   297.1    .045       0   312.1      .1       0
Bank Sta=297.1,312.1
XS Rating Curve= 0 ,0
Exp/Cntr=0.3,0.1

Type RM Length L Ch R = 1 ,6006.4  ,387.6,370.3,353.7
XS GIS Cut Line= 2
     1936205.987      360614.335     1935826.836      360641.713
#Sta/Elev= 30
       0 1455.25     9.8 1451.91    19.5 1448.82    29.2 1446.13    48.7 1441.35
   107.2 1427.37     117 1424.71   126.7 1421.01   136.5 1416.74   145.3  1414.3
   146.2 1414.05     156 1414.07   160.3 1414.93   165.7 1416.01   175.4  1418.4
   185.2 1419.66   194.9 1419.38   224.2 1416.43   243.7 1414.71   253.4 1414.06
   263.2 1413.57   272.9 1413.19   282.7 1413.05   292.4 1413.93   302.2 1416.66
   311.9 1420.58   321.7 1424.76   360.6 1442.57   370.4 1446.51   380.1 1450.06
#Mann= 3 , 0 , 0
       0      .1       0   145.3    .045       0   160.3      .1       0
#XS Ineff= 2 , 0
                          185.35         1419.72
Permanent Ineff=
       F       F
Bank Sta=145.3,160.3
XS Rating Curve= 0 ,0
Exp/Cntr=0.3,0.1

Type RM Length L Ch R = 1 ,5636    ,265,259.4,252.8
XS GIS Cut Line= 2
     1936016.615      360212.304     1935725.817      360546.505
#Sta/Elev= 30
       0 1433.52     9.6 1430.54    28.9 1422.97    38.5 1419.95    48.2 1418.03
    67.4 1416.18      77 1414.74    86.7 1409.55    96.3 1401.54   105.9 1396.14
   115.6 1395.15   144.7 1396.17   163.7 1396.73     183 1395.51   192.6 1396.92
   211.9 1401.36   221.5 1401.47   279.3 1399.52   298.6 1400.04   308.2 1401.74
   317.8 1404.57     366 1420.75   375.6 1423.09   385.2 1424.23   394.8 1424.74
   404.5 1426.35   414.1 1429.08   423.7 1432.77   433.4  1437.9     443 1443.97
#Mann= 3 , 0 , 0
       0      .1       0   105.9    .045       0   144.7      .1       0
Bank Sta=105.9,144.7
XS Rating Curve= 0 ,0
Exp/Cntr=0.3,0.1

Type RM Length L Ch R = 1 ,5376.7  ,384.8,369.1,353.2
XS GIS Cut Line= 2
     1935825.643      360016.991     1935565.226       360468.38
#Sta/Elev= 30
       0 1469.84     9.8 1463.35    19.7 1457.45    29.5  1452.2   127.8 1405.06
   137.7 1400.76   147.5  1398.3   157.3 1397.59     177 1397.39   196.6 1396.46
     236  1392.6   265.5  1390.3   275.3 1388.99     294 1383.68   304.8 1382.52
   314.6 1383.18   324.5 1385.65   344.1 1392.85   373.6 1400.48   383.5 1402.37
   393.3 1403.65     413 1405.09   422.8 1406.34   432.6 1408.51   452.3 1414.11
     472  1418.8   481.8 1422.78   491.6 1427.95   501.5  1432.4   521.1  1440.3
#Mann= 3 , 0 , 0
       0      .1       0     294    .045       0   314.6      .1       0
Bank Sta=294,314.6
XS Rating Curve= 0 ,0
Exp/Cntr=0.3,0.1

Type RM Length L Ch R = 1 ,5007.6  ,211.1,211.2,210.9
XS GIS Cut Line= 3
     1935299.084      360022.513     1935342.247      360262.676
     1935356.525      360353.368
#Sta/Elev= 30
       0 1406.44     9.8 1399.96    19.5 1394.73    29.3 1390.21      39 1385.98
    48.8  1381.4    68.3 1370.68    78.1 1366.58    87.8 1363.53    97.6  1361.9
   107.4 1361.58   126.9 1361.86   156.2 1362.65   165.9 1363.07   172.6 1363.53
   185.4 1364.64   195.2 1365.79     205  1367.2   214.7 1368.86   234.2  1372.4
     244 1374.32   253.2 1376.34   262.4 1378.54   271.6  1380.9   289.9 1385.84
   299.1  1388.6   308.3 1391.69   317.5 1395.12   326.6 1398.97   335.8  1403.2
#Mann= 3 , 0 , 0
       0      .1       0   156.2    .045       0   172.6      .1       0
Bank Sta=156.2,172.6
XS Rating Curve= 0 ,0
Exp/Cntr=0.3,0.1