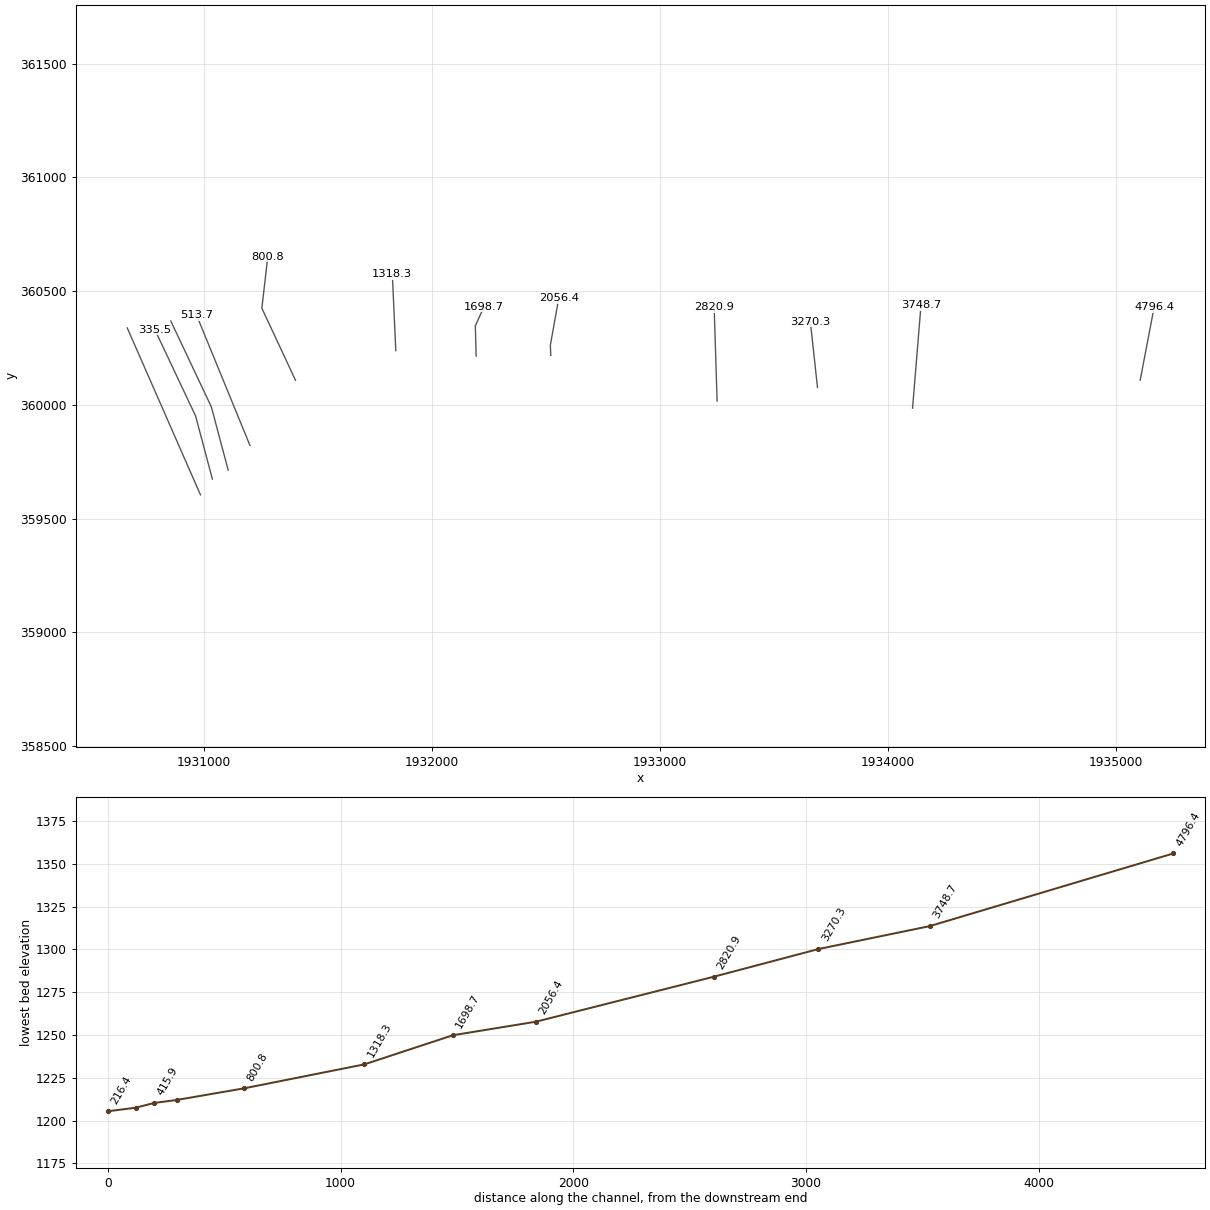
HEC-RAS study DGHTRTYRN.prj: DGHTRTYRN

--- DGHTRTYRN.g01 (geometry) --- (continued)

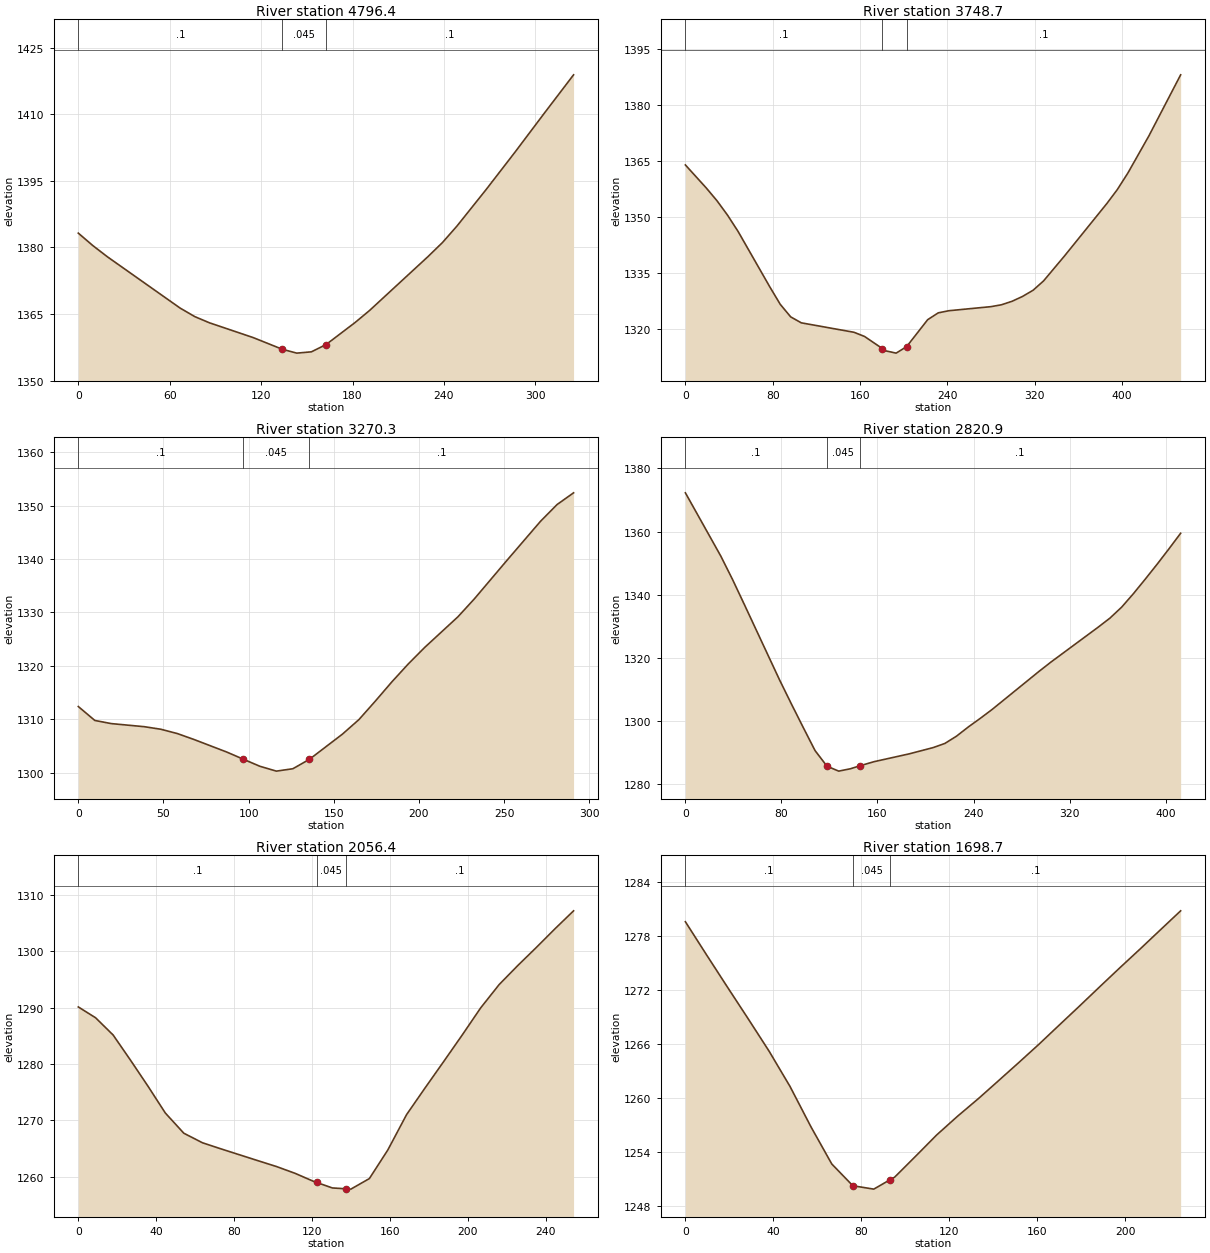
Type RM Length L Ch R = 1 ,4796.4  ,1045.6,1047.6,1050.1
XS GIS Cut Line= 2
     1935107.234      360108.673     1935168.121      360428.041
#Sta/Elev= 20
       0 1383.22     9.6  1380.4    19.1 1377.89    66.9 1366.32    76.5 1364.41
    86.1 1363.02   114.8 1359.69   133.9 1357.06   143.4 1356.19     153 1356.48
   162.6 1358.11   181.7 1363.09   191.2  1365.8   229.5 1377.92   239.1 1381.12
   248.6 1384.83   267.8 1393.08   286.9 1401.57     306 1410.28   325.1 1418.88
#Mann= 3 , 0 , 0
       0      .1       0   133.9    .045       0   162.6      .1       0
Bank Sta=133.9,162.6
XS Rating Curve= 0 ,0
Exp/Cntr=0.3,0.1

Type RM Length L Ch R = 1 ,3748.7  ,473.9,478.4,482.8
XS GIS Cut Line= 2
     1934108.922      359985.751     1934145.956      360437.998
#Sta/Elev= 30
       0 1364.03    19.3 1357.81      29 1354.43    38.6  1350.6    48.3 1346.23
    77.2 1331.47    86.9 1326.73    96.5 1323.36   106.2 1321.77   154.5 1319.24
   164.1 1318.13   180.5 1314.88   183.4 1314.28   193.1 1313.66   202.7 1315.39
     222 1322.61   231.7 1324.44   241.4 1325.01     280  1326.1   289.6  1326.6
   299.3 1327.53   308.9 1328.83   318.6 1330.49   328.2 1332.99   347.6 1339.75
   386.2 1353.71   395.8 1357.45   405.5 1361.89   424.8 1371.86   453.8 1388.15
#Mann= 3 , 0 , 0
       0      .1       0   180.5    .045       0   202.7      .1       0
Bank Sta=180.5,202.7
XS Rating Curve= 0 ,0
Exp/Cntr=0.3,0.1

Type RM Length L Ch R = 1 ,3270.3  ,450.8,449.4,447.9
XS GIS Cut Line= 2
     1933691.963      360076.887     1933660.713       360365.95
#Sta/Elev= 25
       0 1312.36     9.7 1309.75    19.4 1309.16    38.8 1308.58    48.5  1308.1
    58.2 1307.29    67.8  1306.2    87.2 1303.83    96.9 1302.49   106.6 1301.17
   116.3 1300.26     126 1300.71   135.7 1302.47   155.1 1307.19   164.8 1309.92
   174.4 1313.37   184.1 1316.97   193.8 1320.35   203.5 1323.46   222.9 1329.16
   232.6 1332.54     252 1339.85   271.4 1347.05   281.1 1350.18   290.8 1352.38
#Mann= 3 , 0 , 0
       0      .1       0    96.9    .045       0   135.7      .1       0
Bank Sta=96.9,135.7
XS Rating Curve= 0 ,0
Exp/Cntr=0.3,0.1

Type RM Length L Ch R = 1 ,2820.9  ,769.1,764.5,760.1
XS GIS Cut Line= 2
     1933251.858      360016.991     1933238.838      360429.318
#Sta/Elev= 30
       0 1372.28    29.5 1352.23    39.3  1344.8    49.1 1336.89    78.6 1312.86
    88.4 1305.29    98.2 1297.88     108 1290.59   117.9 1285.66   127.7 1284.08
   137.5 1284.83   145.2 1285.76   157.2 1287.08   186.6 1289.57   206.3 1291.53
   216.1 1292.85   225.9 1295.18   235.7 1298.09   245.6  1300.8   255.4  1303.6
   294.7 1315.74   304.5 1318.65   343.8  1329.7   353.6 1332.57   363.4 1336.06
   373.2 1340.34   383.1 1344.96   392.9 1349.65   402.7  1354.5   412.5 1359.47
#Mann= 3 , 0 , 0
       0      .1       0   117.9    .045       0   145.2      .1       0
Bank Sta=117.9,145.2
XS Rating Curve= 0 ,0
Exp/Cntr=0.3,0.1

Type RM Length L Ch R = 1 ,2056.4  ,352.8,357.6,362.2
XS GIS Cut Line= 3
      1932522.49       360217.36     1932520.439      360261.998
     1932557.414       360468.38
#Sta/Elev= 30
       0 1290.14     8.9 1288.21    17.9 1285.15    26.8 1280.69    35.8 1276.06
    44.7  1271.3    54.2 1267.71    63.8 1266.01    73.3 1264.93    82.8 1263.88
    92.3 1262.83   101.9 1261.78   111.4 1260.58   120.9 1259.15   122.4 1258.97
   130.5 1257.99   137.4 1257.84     140 1257.78   149.5 1259.65     159 1264.74
   168.6    1271   178.1 1275.74   187.6  1280.4   197.2 1285.15   206.7 1289.98
   216.2 1294.12   225.8 1297.51   235.3 1300.71   244.8    1304   254.4 1307.21
#Mann= 3 , 0 , 0
       0      .1       0   122.4    .045       0   137.4      .1       0
Bank Sta=122.4,137.4
XS Rating Curve= 0 ,0
Exp/Cntr=0.3,0.1

Type RM Length L Ch R = 1 ,1698.7  ,380,380.5,380.9
XS GIS Cut Line= 3
     1932195.013      360214.363     1932191.567      360347.624
     1932229.477      360431.487
#Sta/Elev= 27
       0 1279.54     9.5 1275.91      19 1272.33    28.6 1268.75    38.1 1265.16
    47.6 1261.25    57.1 1256.78    66.6 1252.64    76.2 1250.22    78.1 1250.15
    85.7 1249.85    93.1 1250.89    95.2 1251.18   104.7 1253.49   114.3 1255.86
   123.8 1257.94   133.3  1259.9   142.5  1261.9   151.7 1263.91   160.9 1265.95
   170.1 1268.07   179.3 1270.18   188.5 1272.32   197.7 1274.44   206.9 1276.52
   216.1 1278.64   225.3 1280.75
#Mann= 3 , 0 , 0
       0      .1       0    76.2    .045       0    93.1      .1       0
Bank Sta=76.2,93.1
XS Rating Curve= 0 ,0
Exp/Cntr=0.3,0.1

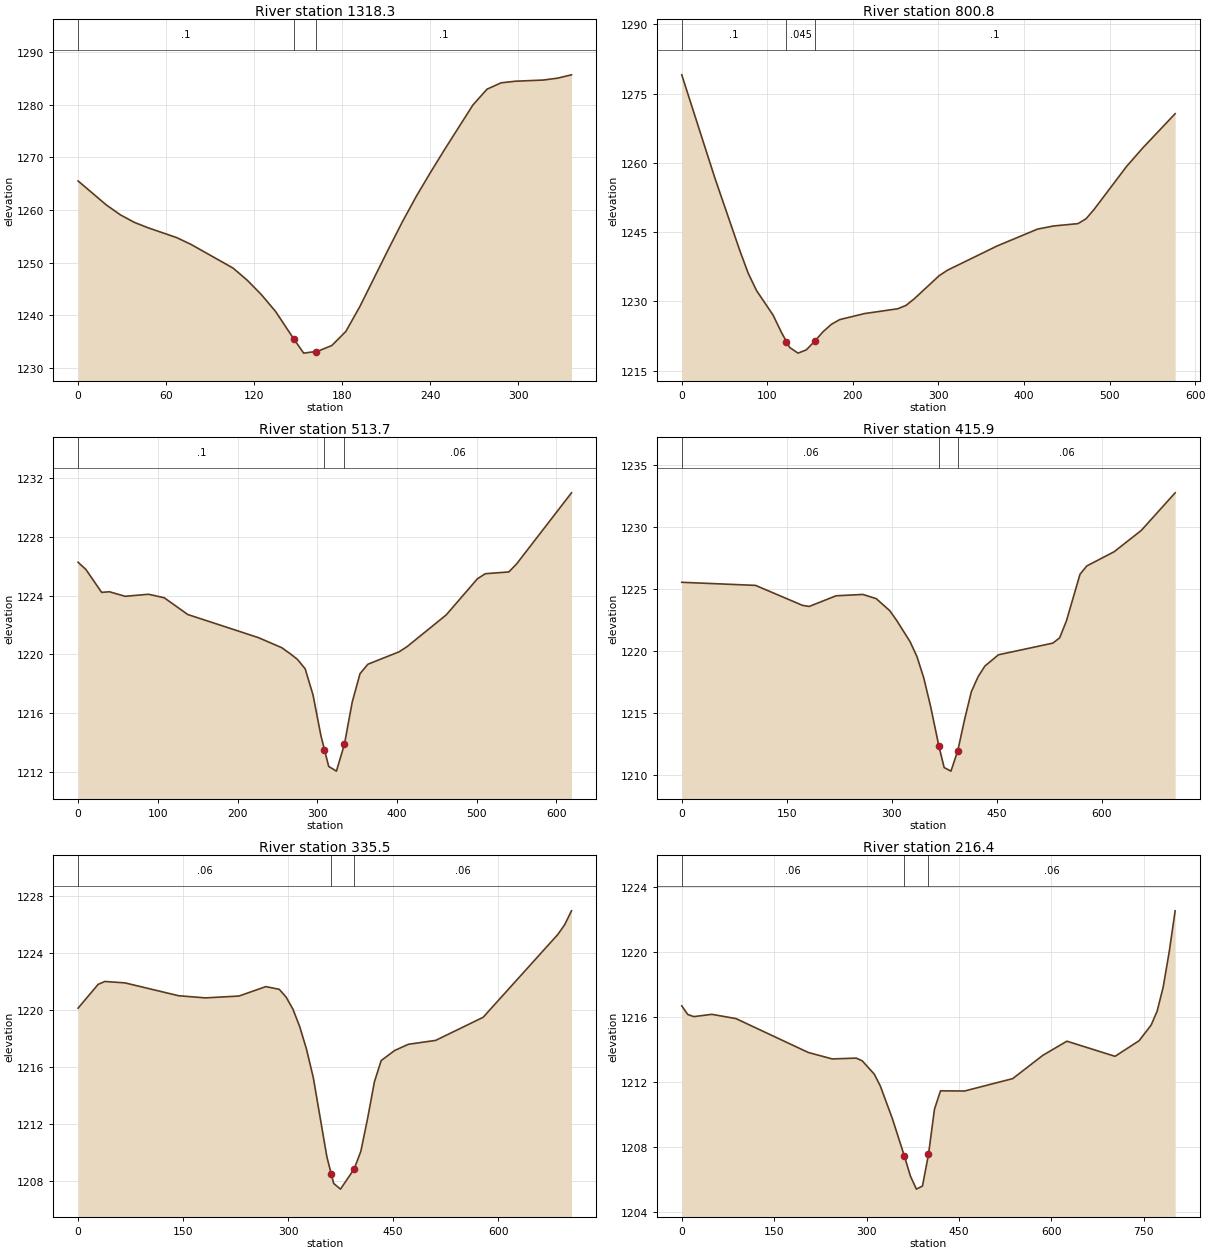
Type RM Length L Ch R = 1 ,1318.3  ,508.5,517.5,526.1
XS GIS Cut Line= 2
     1931842.802      360238.194     1931827.379      360574.283
#Sta/Elev= 30
       0 1265.53    19.2 1260.98    28.8 1259.09    38.4 1257.65    48.1 1256.59
    67.3 1254.75    76.9 1253.48   105.7 1248.96   115.4 1246.64     125 1243.91
   134.6 1240.74   146.9 1235.57   153.8  1232.8   161.9  1233.1   163.4 1233.15
     173 1234.25   182.6 1236.94   192.2  1241.7   211.5 1252.51   221.1 1257.76
   230.7 1262.66   240.3 1267.16   249.9 1271.51   269.2 1279.97   278.8 1282.97
   288.4 1284.18     298 1284.48   317.2 1284.71   326.8 1285.06   336.4  1285.7
#Mann= 3 , 0 , 0
       0      .1       0   146.9    .045       0   161.9      .1       0
Bank Sta=146.9,161.9
XS Rating Curve= 0 ,0
Exp/Cntr=0.3,0.1

Type RM Length L Ch R = 1 ,800.8   ,288.2,287.1,286
XS GIS Cut Line= 3
       1931402.9      360108.137     1931255.331      360424.978
     1931281.372      360650.672
#Sta/Elev= 30
       0 1279.09    38.8 1256.68      68 1240.94    77.7 1236.09    87.4 1232.35
   106.8 1227.01   116.5 1223.28   122.4 1221.29   126.2 1220.01   135.9 1218.79
   145.6  1219.5   155.3 1221.36     165  1223.4   174.8 1225.02   184.5 1226.05
   213.6 1227.36   252.4  1228.4   262.1 1229.13   271.8 1230.57     301 1235.59
   310.7 1236.77   368.4 1241.99   415.8 1245.66   434.7 1246.34   463.1 1246.85
   472.6 1247.91     482 1249.94   519.9 1259.24   538.8 1263.24   576.7 1270.67
#Mann= 3 , 0 , 0
       0      .1       0   122.4    .045       0   155.3      .1       0
Bank Sta=122.4,155.3
XS Rating Curve= 0 ,0
Exp/Cntr=0.3,0.1

Type RM Length L Ch R = 1 ,513.7   ,96.6,97.8,99
XS GIS Cut Line= 2
     1931203.247      359821.679     1930968.872      360394.596
#Sta/Elev= 30
       0 1226.27     9.8 1225.78    29.5 1224.22    39.3 1224.26      59 1223.95
    88.4 1224.09   108.1 1223.85   137.6 1222.71     226 1221.14   255.5 1220.45
   265.3 1220.07   275.1 1219.66   284.9 1219.01   294.8 1217.22   304.6 1214.47
   309.1  1213.5   314.4 1212.36   324.1 1212.04   334.1 1213.86   343.9 1216.74
   353.7 1218.68   363.5 1219.32   402.8 1220.17   412.7 1220.52   461.8 1222.68
   501.1 1225.15   510.9 1225.49   540.4 1225.61   550.2 1226.16     619    1231
#Mann= 3 , 0 , 0
       0      .1       0   309.1    .045       0   334.1     .06       0
Bank Sta=309.1,334.1
XS Rating Curve= 0 ,0
Exp/Cntr=0.3,0.1

Type RM Length L Ch R = 1 ,415.9   ,80.4,80.4,80.3
XS GIS Cut Line= 3
     1931107.761      359713.172     1931033.976       359990.95
     1930856.025      360368.554
#Sta/Elev= 30
       0 1225.52   105.4 1225.27   172.4 1223.66     182 1223.57   220.4 1224.43
   258.7 1224.54   277.8  1224.2   297.1 1223.23   306.8 1222.46   326.2 1220.72
     336 1219.52   345.7  1217.8   355.4 1215.52   367.4 1212.28   374.8 1210.57
   384.5 1210.28   394.2 1211.91   403.9 1214.42   413.6 1216.68   423.3  1217.9
     433 1218.76   452.4 1219.67   530.1 1220.61   539.8 1221.04   549.5 1222.41
   568.9 1226.17   578.6 1226.84   617.5 1227.98   656.3  1229.7   704.8 1232.74
#Mann= 3 , 0 , 0
       0     .06       0   367.4    .045       0   394.2     .06       0
Bank Sta=367.4,394.2
XS Rating Curve= 0 ,0
Exp/Cntr=0.3,0.1

Type RM Length L Ch R = 1 ,335.5   ,119.7,119.1,118.5
XS GIS Cut Line= 3
     1931038.317       359674.11     1930964.532      359951.887
     1930786.581      360329.491
#Sta/Elev= 30
       0 1220.14    28.7 1221.81    38.3 1222.01    67.1 1221.91   143.7 1221.01
     182 1220.86   229.9 1220.99   268.2 1221.65   287.4 1221.46   297.1 1220.92
   306.8 1220.08   316.5 1218.86   326.2 1217.28     336 1215.27   355.4 1209.72
   361.5 1208.55   365.1 1207.86   374.8 1207.46   394.2 1208.86   403.9 1210.11
   413.6 1212.42   423.3 1214.98     433 1216.47   452.4 1217.18   471.9 1217.61
   510.7 1217.88   578.6  1219.5   685.4 1225.31   695.1 1225.99   704.8 1226.96
#Mann= 3 , 0 , 0
       0     .06       0   361.5    .045       0   394.2     .06       0
Bank Sta=361.5,394.2
XS Rating Curve= 0 ,0
Exp/Cntr=0.3,0.1

Type RM Length L Ch R = 1 ,216.4   ,215.9,216.4,216.9
XS GIS Cut Line= 2
     1930986.233      359604.665     1930665.053      360338.172
#Sta/Elev= 30
       0 1216.68     9.8 1216.15    19.5 1216.02    48.8 1216.16    87.9  1215.9
   205.1 1213.82   244.1 1213.42   283.2 1213.47     293  1213.3   312.5 1212.48
   322.2 1211.76   341.8 1209.75   361.3 1207.45   371.1 1206.22   380.8 1205.42
   390.6 1205.61   400.4 1207.55   410.1 1210.33   419.9 1211.46     459 1211.45
   537.1 1212.21   585.9 1213.64     625 1214.51   703.1 1213.58   742.2 1214.54
   761.7  1215.5   771.4 1216.35   781.2 1217.82     791 1219.99   800.7 1222.52
#Mann= 3 , 0 , 0
       0     .06       0   361.3    .045       0   400.4     .06       0
Bank Sta=361.3,400.4
XS Rating Curve= 0 ,0
Exp/Cntr=0.3,0.1

Chan Stop Cuts=-1
Use User Specified Reach Order=0
Composite Channel Slope=5